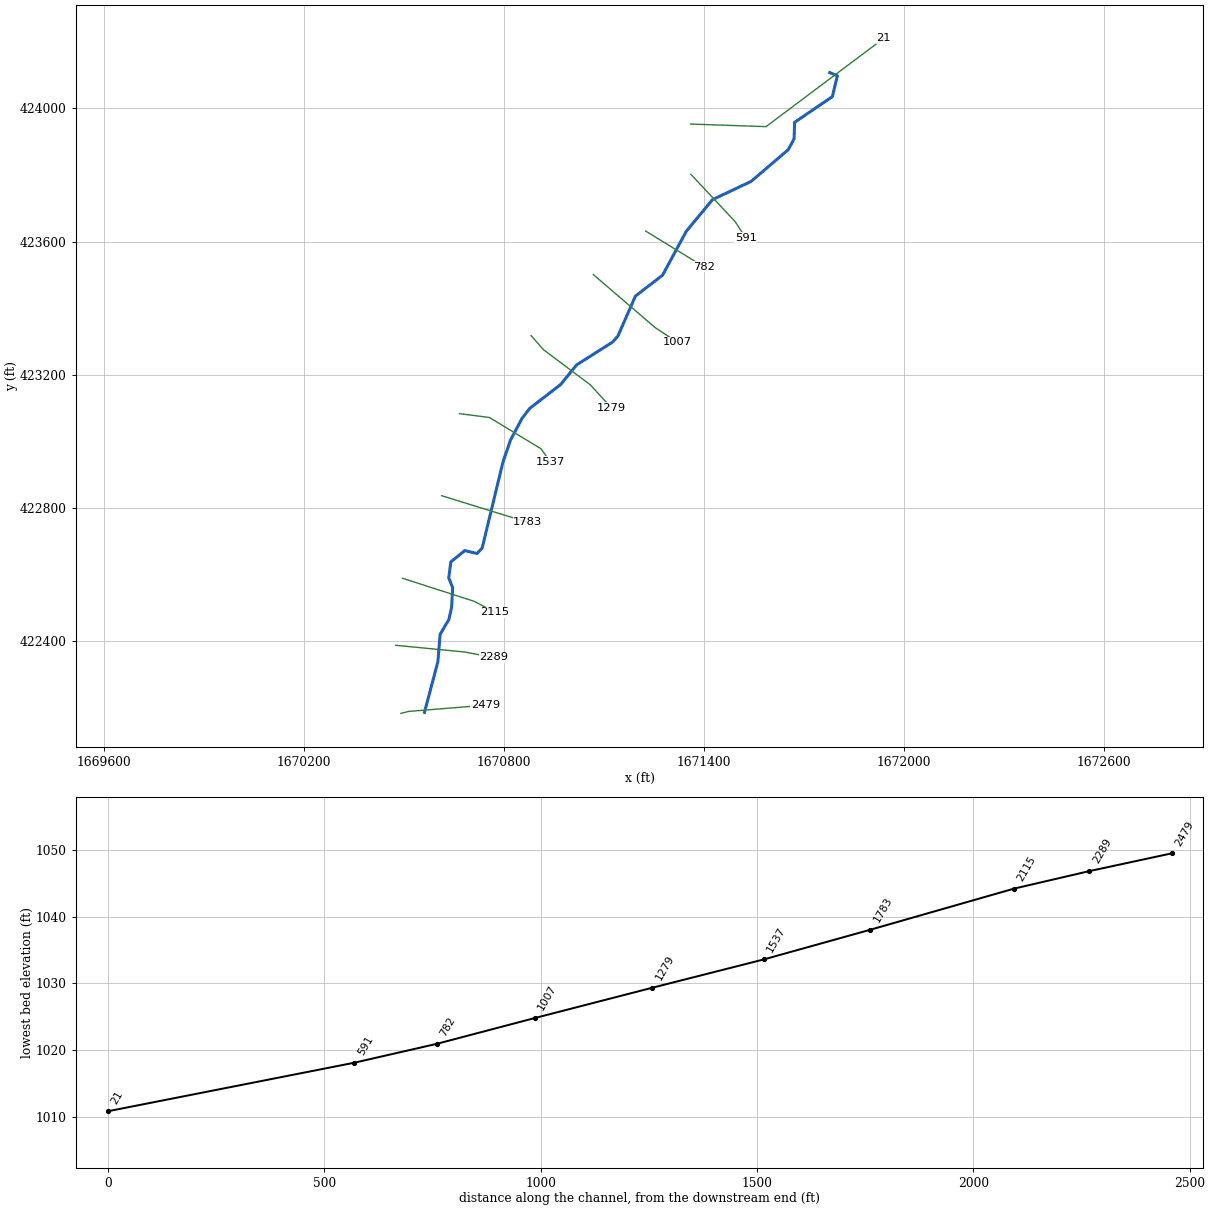
--- CAMPRN.prj (project) ---

Proj Title=CAMPRN
Current Plan=p01
Default Exp/Contr=0.3,0.1
English Units
Geom File=g01
Flow File=f01
Plan File=p01
Y Axis Title=Elevation
X Axis Title(PF)=Main Channel Distance
X Axis Title(XS)=Station
BEGIN DESCRIPTION:
---------- MODELED AS PART OF WVEMD CTP PROGRAM, 2023----------
Stream Name: Camp Run
Flood Zone:  AFH
Wetzel County, WV
HEC-RAS Version: RAS 6.3
Vertical Datum: NAVD88
Projection: NAD 1983 StatePlane West Virginia S FIPS 4702 (US Feet)
Terrain: 1-meter West Virginia FEMA R3 South Central (collected 2018-2020)
Land Use: 2019 NLCD
Hydrologic Method:
WV SIR2010-5033 regression equations
Additional Model Notes:
Shared XS with Knobb Fork
END DESCRIPTION:
DSS Export Rating Curves= 0
DSS Export Rating Curve Sorted= 0
DSS Export Volume Flow Curves= 0
DXF OffsetX= 0
DXF OffsetY= 0
DXF ScaleX= 1
DXF ScaleY= 10

--- CAMPRN.p01 (plan) ---

Plan Title=Floodplain
Program Version=6.30
Short Identifier=Floodplain
Geom File=g01
Flow File=f01
Subcritical Flow
K Sum by GR= 0
Std Step Tol= 0.01
Critical Tol= 0.01
Num of Std Step Trials= 20
Max Error Tol= 0.3
Flow Tol Ratio= 0.001
Split Flow NTrial= 30
Split Flow Tol= 0.02
Split Flow Ratio= 0.02
Log Output Level= 0
Friction Slope Method= 1
Unsteady Friction Slope Method= 2
Unsteady Bridges Friction Slope Method= 1
Parabolic Critical Depth
Global Vel Dist= 0 , 0 , 0
Global Log Level= 0
CheckData=True
Encroach Param=-1 ,0,0, 0
Computation Interval=1MIN
Output Interval=1HOUR
Instantaneous Interval=1HOUR
Mapping Interval=1HOUR
Computation Time Step Use Courant=        0
Computation Time Step Use Time Series=    0
Computation Time Step Count To Double=0
Computation Time Step Max Doubling=0
Computation Time Step Max Halving=0
Computation Time Step Residence Courant=0
Run HTab= 0
Run UNet= 0
Run Sediment= 0
Run PostProcess= 0
Run WQNet= 0
Run RASMapper=-1
UNET Theta= 1
UNET Theta Warmup= 1
UNET ZTol= 0.02
UNET ZSATol= 0.02
UNET MxIter= 20
UNET Max Iter WO Improvement= 0
UNET MaxInSteps= 0
UNET DtIC= 0
UNET DtMin= 0
UNET MaxCRTS= 20
UNET WFStab= 2
UNET SFStab= 1
UNET WFX= 1
UNET SFX= 1
UNET Gravity=32.17405
UNET 1D Methodology=Finite Difference
UNET DSS MLevel= 4
UNET Pardiso=0
UNET DZMax Abort= 100
UNET Use Existing IB Tables=-1
UNET Froude Reduction=False
UNET Froude Limit= 0.8
UNET Froude Power= 4
UNET D1 Cores= 0
UNET WindReference=Eulerian
UNET WindDragFormulation=Hsu (1988)
UNET D2 Coriolis=0
UNET D2 Cores= 0
UNET D2 Theta= 1
UNET D2 Theta Warmup= 1
UNET D2 Z Tol= 0.01
UNET D2 Volume Tol= 0.01
UNET D2 Max Iterations= 20
UNET D2 Equation= 0
UNET D2 RampUpFraction=0.1
UNET D2 TimeSlices= 1
UNET D2 Turbulence Formulation=None
UNET D2 Eddy Viscosity=0.3
UNET D2 Transverse Eddy Viscosity=0.1
UNET D2 Smagorinsky Mixing=0.05
UNET D2 BCVolumeCheck=0
UNET D2 Cores=0
UNET D2 SolverType=PARDISO (Direct)
UNET D2 Minimum Iterations= 3
UNET D2 Maximum Iterations= 30
UNET D2 Restart Number= 10
UNET D2 Relaxation Coeff=1.3
UNET D2 SOR Precondition Iterations= 10
UNET D2 ILUT Maximum Fill= 8
UNET D2 ILUT Tolerance=1E-08
UNET D2 Convergence Tolerance=0.00001
UNET D1D2 MaxIter= 0
UNET D1D2 ZTol=0.01
UNET D1D2 QTol=0.1
UNET D1D2 MinQTol=1
Write IC File= 0
Write IC File at Fixed DateTime=0
Write IC File at Sim End=0
Echo Input=False
Echo Parameters=False
Echo Output=False
Write Detailed= 0
HDF Write Warmup=0
HDF Write Time Slices=0
HDF Flush=0
HDF Compression= 1
HDF Chunk Size= 1
HDF Spatial Parts= 1
HDF Use Max Rows=0
HDF Fixed Rows= 1
Calibration Method= 0
Calibration Iterations= 20
Calibration Max Change=0.05
Calibration Tolerance=0.2
Calibration Maximum=1.5
Calibration Minimum=0.5
Calibration Optimization Method= 1
WQ AD Non Conservative
WQ ULTIMATE=-1
WQ Max Comp Step=1HOUR
WQ Output Interval=15MIN
WQ Output Selected Increments= 0
WQ Output face flow=0
WQ Output face velocity=0
WQ Output face area=0
WQ Output face dispersion=0
WQ Output cell volume=0
WQ Output cell surface area=0
WQ Output cell continuity=0
WQ Output cumulative cell continuity=0
WQ Output face conc=0
WQ Output face dconc_dx=0
WQ Output face courant=0
WQ Output face peclet=0
WQ Output face adv mass=0
WQ Output face disp mass=0
WQ Output cell mass=0
WQ Output cell source sink temp=0
WQ Output nsm pathways=0
WQ Output nsm derived pathways=0
WQ Create Restart=0
WQ Fixed Restart=0
WQ System Summary=0
WQ Write To DSS=0
Sorting and Armoring Iterations= 10
XS Update Threshold= 0.02
Bed Roughness Predictor= 0
Hydraulics Update Threshold= 0.02
Energy Slope Method= 1
Volume Change Method= 1
Sediment Retention Method= 0
Sediment TS Multiplier= 1
Warm Up Method= 0
XS Weighting Method= 0
Number of US Weighted Cross Sections= 1
Number of DS Weighted Cross Sections= 1
Upstream XS Weight=0
Main XS Weight=1
Downstream XS Weight=0
Number of DS XS's Weighted with US Boundary= 1
Upstream Boundary Weight= 1
Weight of XSs Associated with US Boundary= 0
Number of US XS's Weighted with DS Boundary= 1
Downstream Boundary Weight= 0.5
Weight of XSs Associated with DS Boundary= 0.5
Percentile Method= 0
Sediment Output Level= 3
Mass or Volume Output= 0
Output Increment Type= 1
Profile and TS Output Increment= 1
Transport Output Increment 1
XS Output Flag= 0
XS Output Increment= 10
Read HDF5 Sediment Hotstart= 0
Sediment Hotstart Type= 0
Write Gradation File= 0
Read Gradation Hotstart= 0
Write HDF5 File= 1
Write Binary Output= 1
Write DSS Sediment File= 0
DSS Sediment Output Type= 1
SV Curve= 0
Specific Gage Flag= 0
Subcell Erosion Methods= 0
Subcell Deposition Methods= 0
Advection Scheme= 1
Matrix Solver= 0
Implicit Weighting Factor= 1
Maximum Outer Loop Convergence Iterations= 5
Convergence Maximum Absolute= 0.001
Convergence RMSE= 0.0001
Grain Fractions Max Abs Error= 0.001
Max Subgrid Regions= 1
Max Subgrid Length Scale= 3.402823E+38
Initial Layer Thickness= 3.402823E+38
Min Layer Thickness= 3.402823E+38
Max Layer Thickness= 3.402823E+38
Number of Layers= 5

--- CAMPRN.f01 (steady flow) ---

Flow Title=Flow
Program Version=6.31
Number of Profiles= 1
Profile Names=F01pct
River Rch & RM=CAMPRN,Main            ,2479
     657
Boundary for River Rch & Prof#=CAMPRN,Main            , 1
Up Type= 0
Dn Type= 3
Dn Slope=0.01279
DSS Import GetInterval= 0
DSS Import GetPeak= 0
DSS Import FillOption= 0

--- CAMPRN.g01 (geometry) ---

Geom Title=Geometry
Program Version=6.31

River Reach=CAMPRN          ,Main
Reach XY= 30
1670562.40010209422185.3963548841670602.68759415422338.026576787
 1670609.3806387422419.8959460711670635.64139742422464.604345173
1670643.88857785422501.9336881341670646.92771174422559.930865511
1670635.13836999422589.4042198511670641.56892002422637.633345097
1670683.26409237422671.5290020261670719.99326579422662.776439384
1670735.38468704422679.1608555471670797.62484509 422936.93398717
1670820.20619519423003.2051942051670855.26989393423069.363116354
1670878.20194125423098.8584354821670970.59987818423170.371907219
1671018.41139585423229.2733541731671126.51750517423298.075400218
1671142.48640102423316.2224921141671194.91796292423436.024293914
1671276.23607264423498.8939987871671347.61517802423631.041801974
1671425.79823481 423725.742886351671541.90538821423780.819356546
1671653.55049028423876.3592092391671670.69384688423908.814306548
1671672.32099959423958.3490010951671785.53799962424035.448001102
 1671800.4709996424098.3070011141671777.54999959424107.684001088

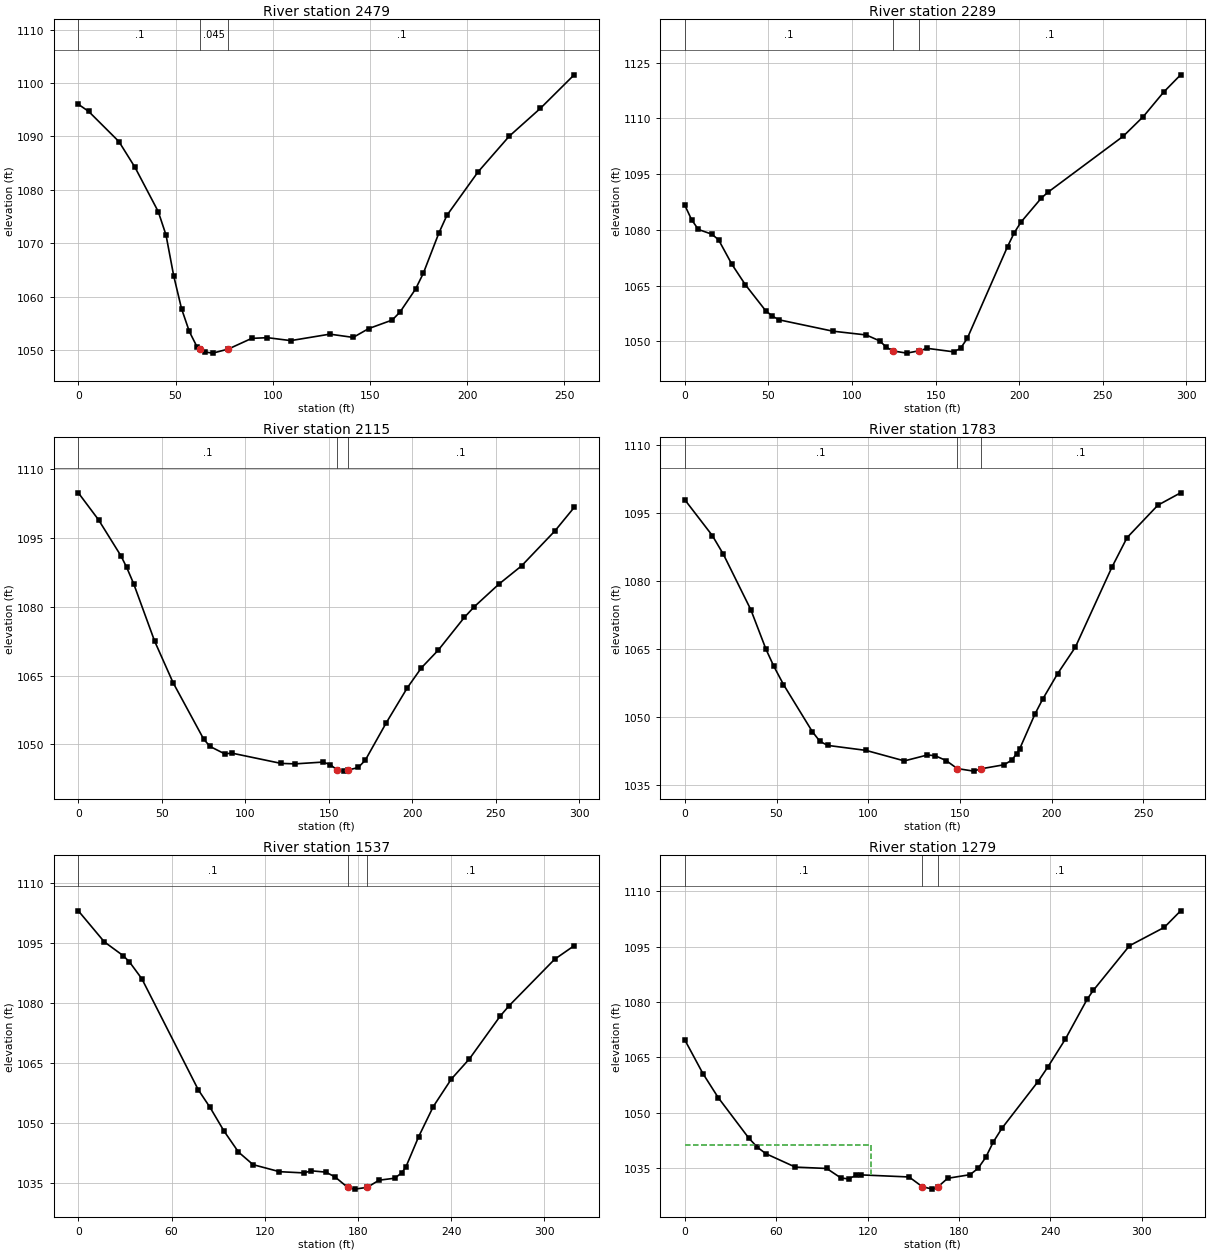
Type RM Length L Ch R = 1 ,2479    ,190.2,189.8,187.8
XS GIS Cut Line= 4
1670491.82278003422182.425888975 1670515.3455968422188.306593167
1670651.33688125422199.3329135281670745.42814832 422207.05133778
#Sta/Elev= 30
       0 1096.02     5.3 1094.69    20.9 1089.04    29.2  1084.2    41.1 1075.96
    45.1 1071.59    49.1 1063.88    53.1 1057.79    57.1 1053.53    61.1 1050.63
    62.8 1050.23    65.1 1049.69    69.2 1049.48    77.2 1050.25    89.2 1052.24
    97.3 1052.37   109.3 1051.82   129.4 1053.03   141.4 1052.42   149.4 1054.07
   161.5 1055.67   165.5 1057.16   173.5 1061.46   177.5 1064.42   185.5 1071.94
   189.6 1075.23   205.6 1083.35   221.7 1090.05   237.7 1095.25   255.1 1101.53
#Mann= 3 ,-1,0
       0      .1       0    62.8    .045       0    77.2      .1       0
Bank Sta=62.8,77.2
XS Rating Curve= 0 ,0
Exp/Cntr(USF)=0,0
Exp/Cntr=0.3,0.1

Type RM Length L Ch R = 1 ,2289    ,176,174.4,172.7
XS GIS Cut Line= 3
1670476.03772451 422386.981873481670682.13419728422366.925505325
1670769.96725782 422350.32713168
#Sta/Elev= 30
       0 1086.64     4.1 1082.72     8.1 1080.12    16.2 1078.84    20.2 1077.33
    28.2 1070.71    36.2 1065.25    48.3 1058.28    52.3 1056.81    56.3  1055.8
    88.5 1052.74   108.5 1051.72   116.6 1050.11   120.6 1048.38   124.7 1047.41
   132.7 1046.83   139.8 1047.43   145.1 1048.11   160.8 1047.18   164.9 1048.12
   168.9 1050.79     193 1075.51     197 1079.22     201 1082.08   213.2 1088.56
   217.2 1090.15   262.2 1105.22   274.2 1110.51   286.4 1117.11   296.5 1121.74
#Mann= 3 ,-1,0
       0      .1       0   124.7    .045       0   139.8      .1       0
Bank Sta=124.7,139.8
XS Rating Curve= 0 ,0
Exp/Cntr(USF)=0,0
Exp/Cntr=0.3,0.1

Type RM Length L Ch R = 1 ,2115    ,328.9,332.2,331.5
XS GIS Cut Line= 3
1670496.60344544422588.3524808361670712.05170861422518.946328943
1670774.22805301422485.689214495
#Sta/Elev= 30
       0 1104.74    12.1 1098.87    25.5 1091.04    28.9 1088.56    33.1    1085
    45.7 1072.46    56.7 1063.47    75.1 1051.13    78.9 1049.56    87.7 1047.95
    91.9 1048.12   121.4 1045.88   129.8 1045.78   146.6 1046.17   150.8 1045.61
     155 1044.46   159.2  1044.2   161.6 1044.43   167.6 1044.99   171.8 1046.56
   184.4 1054.72     197 1062.33   205.4 1066.66   215.6 1070.55   231.1 1077.62
     237 1079.93   251.8 1084.87   265.4 1088.85   285.4 1096.46   296.9 1101.56
#Mann= 3 ,-1,0
       0      .1       0     155    .045       0   161.6      .1       0
Bank Sta=155,161.6
XS Rating Curve= 0 ,0
Exp/Cntr(USF)=0,0
Exp/Cntr=0.3,0.1

Type RM Length L Ch R = 1 ,1783    ,247.6,246.3,244.5
XS GIS Cut Line= 2
1670613.76175469422836.4568868581670871.95867806422756.538791528
#Sta/Elev= 30
       0    1098      15 1090.09      21 1085.98      36  1073.7    44.3 1064.93
    48.5 1061.24    53.8 1057.17    69.5 1046.78    73.6 1044.65    77.8 1043.73
    98.8 1042.62   119.7  1040.3   132.3 1041.61   136.5 1041.44   142.5 1040.37
   148.5 1038.61   157.4 1038.04   161.7 1038.57   174.1 1039.45   178.3 1040.49
   180.9 1041.91   182.5  1042.9   190.9 1050.66   195.1 1053.94   203.3 1059.61
   212.9 1065.42   232.8 1083.06   241.1 1089.63   257.9  1096.8   270.3 1099.53
#Mann= 3 ,-1,0
       0      .1       0   148.5    .045       0   161.7      .1       0
Bank Sta=148.5,161.7
XS Rating Curve= 0 ,0
Exp/Cntr(USF)=0,0
Exp/Cntr=0.3,0.1

Type RM Length L Ch R = 1 ,1537    ,257.5,257,255.9
XS GIS Cut Line= 4
 1670667.5651979423082.9486562391670757.21481076423071.380964257
1670911.93269102422977.3934669031670939.40595948422938.352506463
#Sta/Elev= 30
       0 1102.98    16.7 1095.25    28.8 1091.82    32.8  1090.3    40.9 1086.03
    77.2 1058.37    84.8 1053.96    93.8 1048.06   103.1 1042.83   112.5 1039.69
   129.5 1037.94   145.3 1037.63   149.9 1038.16   159.3 1037.83   165.2 1036.65
   173.3 1034.05     178 1033.59     1861034.035   193.6 1035.82   203.7 1036.31
   208.1 1037.63   210.8 1039.05   219.1 1046.67   228.5 1054.17   240.1 1061.02
   251.8 1066.08   271.7 1076.79   277.4 1079.35   306.6 1090.89   319.2 1094.28
#Mann= 3 ,-1,0
       0      .1       0   173.3    .045       0     186      .1       0
Bank Sta=173.3,186
XS Rating Curve= 0 ,0
Exp/Cntr(USF)=0,0
Exp/Cntr=0.3,0.1

Type RM Length L Ch R = 1 ,1279    ,271.9,272.3,271.5
XS GIS Cut Line= 4
1670881.97446209423317.504087011 1670919.5427975 423274.81279677
1671059.57022949423169.7922227791671122.75333905423100.632332589
#Sta/Elev= 30
       0 1069.76    11.9 1060.64      22  1054.1    41.9 1043.24    47.5 1040.75
    53.2 1038.96    72.6 1035.32    93.2 1034.95   102.6 1032.36   107.5 1032.14
   112.6 1033.12     116 1033.21   147.3 1032.65     156 1030.01   162.6 1029.36
   166.3    1030   172.6 1032.29   187.3 1033.27   192.6 1034.99   197.6 1037.94
   202.6 1042.13   208.3 1045.86   231.9 1058.45   238.6 1062.54   249.9 1069.96
   264.3 1080.82   268.3 1083.18     292 1095.24   314.9 1100.22   325.6 1104.69
#Mann= 3 ,-1,0
       0      .1       0     156    .045       0   166.3      .1       0
#XS Ineff= 2 , 0
          122.58 1041.32
Permanent Ineff=
       F       F
Bank Sta=156,166.3
XS Rating Curve= 0 ,0
Exp/Cntr(USF)=0,0
Exp/Cntr=0.3,0.1

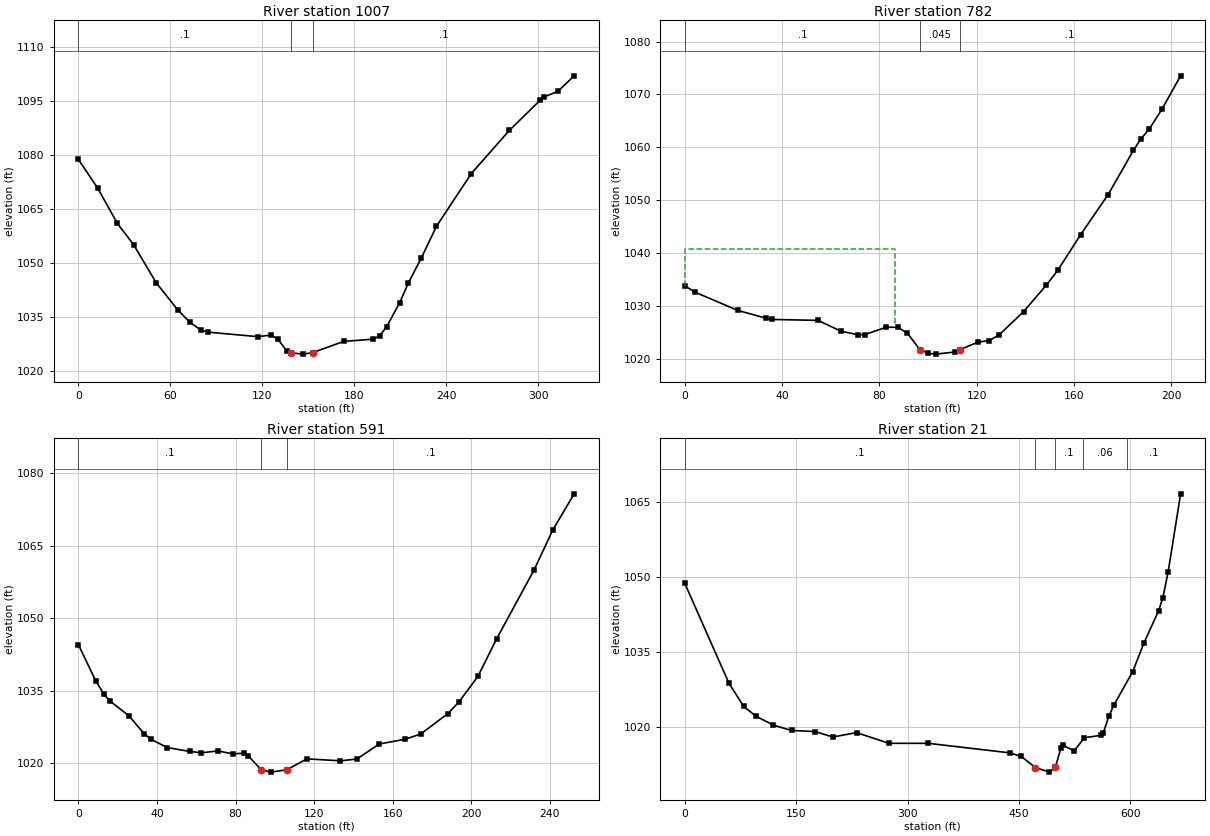
Type RM Length L Ch R = 1 ,1007    ,222.6,224.9,225.6
XS GIS Cut Line= 3
1671068.81100301423500.7521632541671253.60488242  423341.9855908
1671319.97451517423297.739168969
#Sta/Elev= 30
       0 1078.84    12.6 1070.88    25.4 1061.11      36 1055.21    50.7 1044.67
    64.9 1037.05    72.9 1033.61    80.1 1031.44    84.8  1030.9     117 1029.66
   125.6 1030.09   130.1 1028.98   135.8 1025.78   138.6 1025.17   146.7 1024.81
   152.8 1025.22   173.1 1028.34   192.5 1028.97   196.7 1029.96   201.1 1032.42
   209.6 1039.09   215.2  1044.5   223.7 1051.46   233.6 1060.28   256.3  1074.9
   281.1 1086.87   301.3 1095.28   303.9 1096.19   312.8 1097.71   323.4 1102.02
#Mann= 3 ,-1,0
       0      .1       0   138.6    .045       0   152.8      .1       0
Bank Sta=138.6,152.8
XS Rating Curve= 0 ,0
Exp/Cntr(USF)=0,0
Exp/Cntr=0.3,0.1

Type RM Length L Ch R = 1 ,782     ,193.5,191.3,189.7
XS GIS Cut Line= 2
 1671225.4650556423631.735693113 1671399.1332243423524.922084932
#Sta/Elev= 30
       0 1033.87     4.3 1032.65    21.7 1029.24    33.3 1027.76      36 1027.52
    54.8 1027.34    64.2  1025.3    71.1 1024.65      74 1024.65    82.8 1026.05
    87.6 1026.04    91.5 1024.95    96.71021.807   100.2 1021.12   103.1 1020.97
   111.1 1021.37     113 1021.79   120.5 1023.22   125.2 1023.54   129.3 1024.62
   139.3 1028.99   148.7 1034.01   153.4 1036.81   162.8 1043.54   174.1  1051.1
   184.5 1059.46   187.4 1061.51     191 1063.47   196.2  1067.2   203.9 1073.52
#Mann= 3 ,-1,0
       0      .1       0    96.7    .045       0     113      .1       0
#XS Ineff= 2 , 0
           86.45 1040.77
Permanent Ineff=
       F       F
Bank Sta=96.7,113
XS Rating Curve= 0 ,0
Exp/Cntr(USF)=0,0
Exp/Cntr=0.3,0.1

Type RM Length L Ch R = 1 ,591     ,542.6,569.5,580
XS GIS Cut Line= 3
1671361.23772989423802.0692113441671494.05507731423659.764910542
1671525.36202348 423611.38144827
#Sta/Elev= 30
       0 1044.56     8.8 1037.08      13 1034.27    15.9 1032.91    25.8 1029.78
    33.5 1026.08    37.1  1024.9    45.3 1023.21    56.8 1022.41    62.6 1022.14
      71 1022.51    78.7 1021.92    84.2 1022.03    86.3 1021.57    93.11018.618
      98 1018.13   106.1 1018.62   116.3 1020.88   133.4 1020.47   141.8 1020.85
   153.1 1023.96   166.2 1024.93   174.2 1026.02   188.1 1030.27   193.6 1032.64
   203.3 1037.94   212.8  1045.7   231.9    1060   241.4 1068.26   252.3 1075.77
#Mann= 3 ,-1,0
       0      .1       0    93.1    .045       0   106.1      .1       0
Bank Sta=93.1,106.1
XS Rating Curve= 0 ,0
Exp/Cntr(USF)=0,0
Exp/Cntr=0.3,0.1

Type RM Length L Ch R = 1 ,21      ,66.1,,58.2
XS GIS Cut Line= 3
1671360.89552879423953.0332802621671586.64168119423945.315463085
  1671939.731817424210.615428514
#Sta/Elev= 30
       0 1048.74    59.3 1028.74    79.3 1024.05    95.3 1022.13   119.3 1020.29
   143.7 1019.22   175.3    1019   199.3 1017.91   231.2 1018.79   274.9 1016.64
   327.8 1016.64   437.9 1014.72   452.9    1014   472.1 1011.77   490.9 1010.86
   498.8  1011.8   506.3 1015.67   509.2 1016.27   524.2 1015.11   537.9 1017.77
   560.6 1018.25   563.5 1018.79   570.8 1022.05   577.5 1024.28     603 1031.02
     618 1036.74   637.8 1043.23   643.5 1045.81   650.8 1051.12   667.5 1066.71
#Mann= 5 ,-1,0
       0      .1       0   472.1    .045       0   498.8      .1       0
  535.88     .06       0  595.88      .1       0
Bank Sta=472.1,498.8
XS Rating Curve= 0 ,0
Exp/Cntr(USF)=0,0
Exp/Cntr=0.3,0.1
LCMann Table=0

Chan Stop Cuts=-1
Use User Specified Reach Order=0
Composite Channel Slope=5